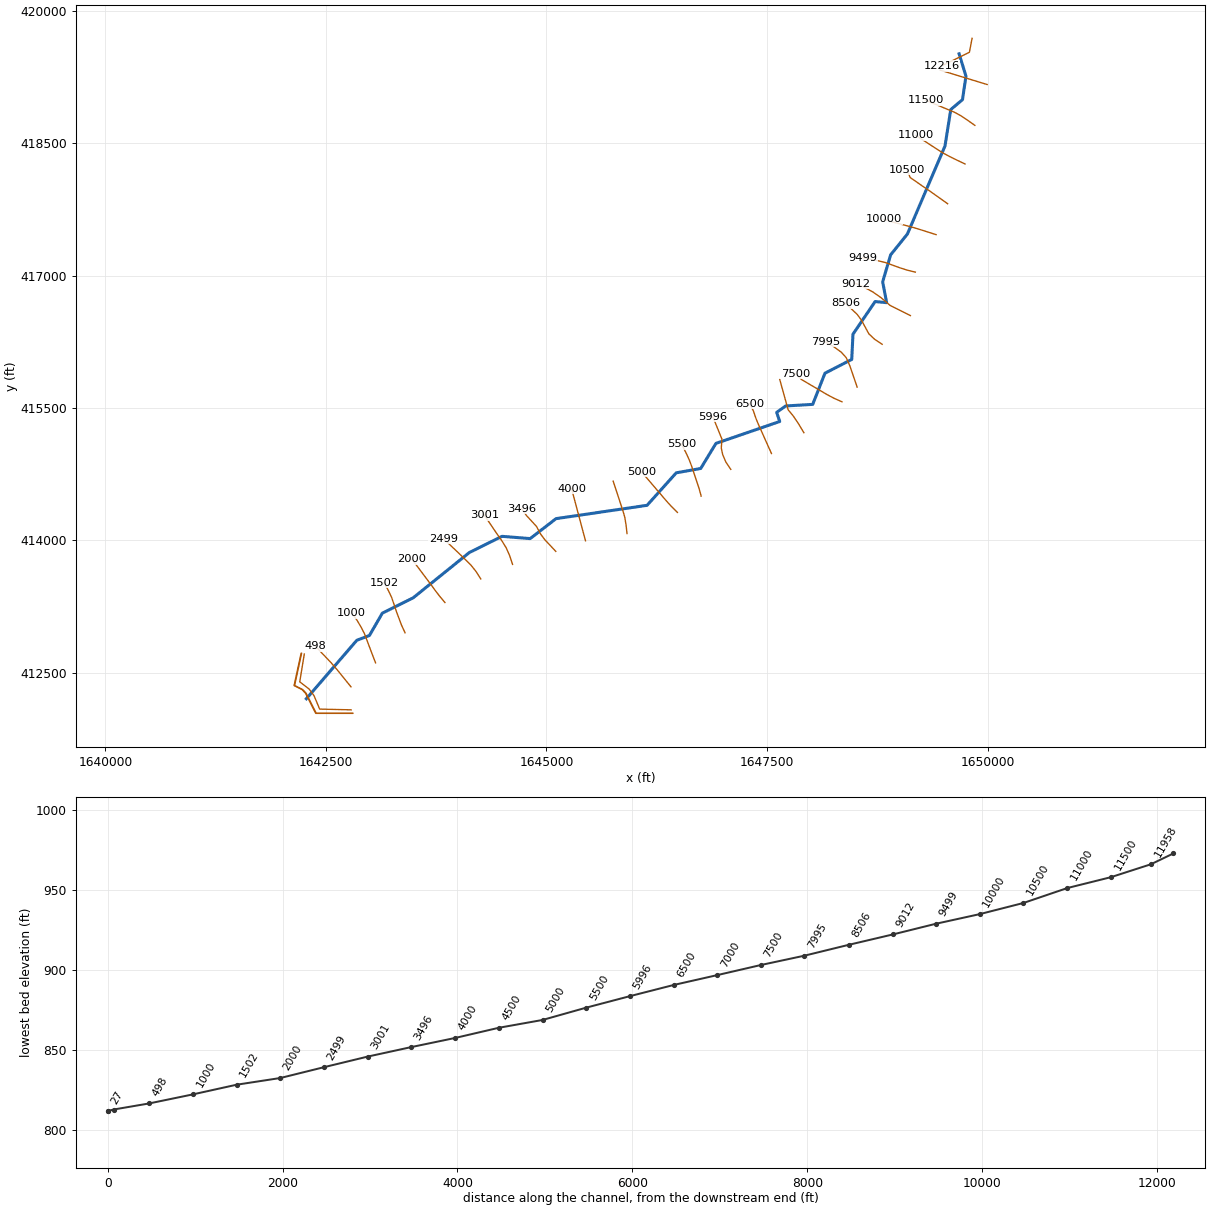
--- STEELRN.prj (project) ---

Proj Title=STEELRN
Current Plan=p01
Default Exp/Contr=0,0
English Units
Geom File=g01
Flow File=f01
Plan File=p01
BEGIN DESCRIPTION:
---------- MODELED AS PART OF WVEMD CTP PROGRAM, 2023----------
Stream Name: Steel Run
Flood Zone:  AFH
Wetzel County, WV
HEC-RAS Version: RAS 6.3
Vertical Datum: NAVD88
Projection: NAD 1983 StatePlane West Virginia S FIPS 4702 (US Feet)
Terrain: 1-meter West Virginia FEMA R3 South Central (collected 2018-2020)
Land Use: 2019 NLCD
Hydrologic Method:
WV SIR2010-5033 regression equations
Model notes:
Leveraged XS
END DESCRIPTION:
DSS Export Rating Curves= 0
DSS Export Rating Curve Sorted= 0
DSS Export Volume Flow Curves= 0
DXF OffsetX= 0
DXF OffsetY= 0
DXF ScaleX= 0
DXF ScaleY= 0

--- STEELRN.p01 (plan) ---

Plan Title=Floodplain
Program Version=6.30
Short Identifier=Floodplain
Geom File=g01
Flow File=f01
Subcritical Flow
K Sum by GR= 0
Std Step Tol= 0.01
Critical Tol= 0.01
Num of Std Step Trials= 20
Max Error Tol= 0.3
Flow Tol Ratio= 0.001
Split Flow NTrial= 30
Split Flow Tol= 0.02
Split Flow Ratio= 0.02
Log Output Level= 0
Friction Slope Method= 1
Unsteady Friction Slope Method= 2
Unsteady Bridges Friction Slope Method= 1
Parabolic Critical Depth
Global Vel Dist= 0 , 0 , 0
Global Log Level= 0
CheckData=True
Encroach Param=-1 ,0,0, 0
Mapping Interval=1HOUR
Computation Time Step Use Courant=        0
Computation Time Step Use Time Series=    0
Computation Time Step Count To Double=0
Computation Time Step Max Doubling=0
Computation Time Step Max Halving=0
Computation Time Step Residence Courant=0
Run HTab= 0
Run UNet= 0
Run Sediment= 0
Run PostProcess= 0
Run WQNet= 0
Run RASMapper= 0
UNET Theta= 0
UNET Theta Warmup= 0
UNET ZTol= 0
UNET ZSATol= 0
UNET MxIter= 0
UNET Max Iter WO Improvement= 0
UNET MaxInSteps= 0
UNET DtIC= 0
UNET DtMin= 0
UNET MaxCRTS= 0
UNET WFStab= 0
UNET SFStab= 0
UNET WFX= 1
UNET SFX= 1
UNET Gravity=32.17405
UNET 1D Methodology=Finite Difference
UNET DSS MLevel= 1
UNET Pardiso=0
UNET DZMax Abort= 0
UNET Use Existing IB Tables= 0
UNET Froude Reduction=False
UNET Froude Limit= 0
UNET Froude Power= 0
UNET D1 Cores= 0
UNET WindReference=Eulerian
UNET WindDragFormulation=Hsu (1988)
UNET D2 Coriolis=0
UNET D2 Cores= 0
UNET D2 Theta= 1
UNET D2 Theta Warmup= 1
UNET D2 Z Tol= 0.01
UNET D2 Volume Tol= 0.01
UNET D2 Max Iterations= 20
UNET D2 Equation= 0
UNET D2 RampUpFraction=0.1
UNET D2 TimeSlices= 1
UNET D2 Turbulence Formulation=Non-Conservative (original)
UNET D2 Eddy Viscosity=0.3
UNET D2 Transverse Eddy Viscosity=0.1
UNET D2 Smagorinsky Mixing=0
UNET D2 BCVolumeCheck=0
UNET D2 Cores=0
UNET D2 SolverType=PARDISO (Direct)
UNET D2 Minimum Iterations= 3
UNET D2 Maximum Iterations= 30
UNET D2 Restart Number= 10
UNET D2 Relaxation Coeff=1.3
UNET D2 SOR Precondition Iterations= 10
UNET D2 ILUT Maximum Fill= 8
UNET D2 ILUT Tolerance=1E-08
UNET D2 Convergence Tolerance=0.00001
UNET D1D2 MaxIter= 0
UNET D1D2 ZTol=0.01
UNET D1D2 QTol=0.1
UNET D1D2 MinQTol=1
Write IC File= 0
Write IC File at Fixed DateTime=0
Write IC File at Sim End=0
Echo Input=False
Echo Parameters=False
Echo Output=False
Write Detailed= 0
HDF Write Warmup=0
HDF Write Time Slices=0
HDF Flush=0
HDF Compression= 1
HDF Chunk Size= 1
HDF Spatial Parts= 1
HDF Use Max Rows=0
HDF Fixed Rows= 1
Calibration Method= 0
Calibration Iterations= 20
Calibration Max Change=0.05
Calibration Tolerance=0.2
Calibration Maximum=1.5
Calibration Minimum=0.5
Calibration Optimization Method= 1
WQ AD Non Conservative
WQ ULTIMATE=-1
WQ Max Comp Step=1HOUR
WQ Output Interval=15MIN
WQ Output Selected Increments= 0
WQ Output face flow=0
WQ Output face velocity=0
WQ Output face area=0
WQ Output face dispersion=0
WQ Output cell volume=0
WQ Output cell surface area=0
WQ Output cell continuity=0
WQ Output cumulative cell continuity=0
WQ Output face conc=0
WQ Output face dconc_dx=0
WQ Output face courant=0
WQ Output face peclet=0
WQ Output face adv mass=0
WQ Output face disp mass=0
WQ Output cell mass=0
WQ Output cell source sink temp=0
WQ Output nsm pathways=0
WQ Output nsm derived pathways=0
WQ Create Restart=0
WQ Fixed Restart=0
WQ System Summary=0
WQ Write To DSS=0
Sorting and Armoring Iterations= 10
XS Update Threshold= 0.02
Bed Roughness Predictor= 0
Hydraulics Update Threshold= 0.02
Energy Slope Method= 1
Volume Change Method= 1
Sediment Retention Method= 0
Sediment TS Multiplier= 1
Warm Up Method= 0
XS Weighting Method= 0
Number of US Weighted Cross Sections= 1
Number of DS Weighted Cross Sections= 1
Upstream XS Weight=0
Main XS Weight=1
Downstream XS Weight=0
Number of DS XS's Weighted with US Boundary= 1
Upstream Boundary Weight= 1
Weight of XSs Associated with US Boundary= 0
Number of US XS's Weighted with DS Boundary= 1
Downstream Boundary Weight= 0.5
Weight of XSs Associated with DS Boundary= 0.5
Percentile Method= 0
Sediment Output Level= 3
Mass or Volume Output= 0
Output Increment Type= 1
Profile and TS Output Increment= 1
Transport Output Increment 1
XS Output Flag= 0
XS Output Increment= 10
Read HDF5 Sediment Hotstart= 0
Sediment Hotstart Type= 0
Write Gradation File= 0
Read Gradation Hotstart= 0
Write HDF5 File= 1
Write Binary Output= 1
Write DSS Sediment File= 0
DSS Sediment Output Type= 1
SV Curve= 0
Specific Gage Flag= 0
Subcell Erosion Methods= 0
Subcell Deposition Methods= 0
Advection Scheme= 1
Matrix Solver= 0
Implicit Weighting Factor= 1
Maximum Outer Loop Convergence Iterations= 5
Convergence Maximum Absolute= 0.001
Convergence RMSE= 0.0001
Grain Fractions Max Abs Error= 0.001
Max Subgrid Regions= 1
Max Subgrid Length Scale= 3.402823E+38
Initial Layer Thickness= 3.402823E+38
Min Layer Thickness= 3.402823E+38
Max Layer Thickness= 3.402823E+38
Number of Layers= 5

--- STEELRN.f01 (steady flow) ---

Flow Title=Flow
Program Version=4.00
Number of Profiles=1
Profile Names=F01pct
River Rch & RM=STEELRN,Main,12216
     647
River Rch & RM=STEELRN,Main,10500
     720
River Rch & RM=STEELRN,Main,8506
     896
River Rch & RM=STEELRN,Main,5996
    1030
River Rch & RM=STEELRN,Main,4000
    1150
Boundary for River Rch & Prof#=STEELRN,Main      ,1
Up Type=0
Dn Type=3
Dn Slope=0.016188

--- STEELRN.g01 (geometry) ---

Geom Title=Geometry
Program Version=6.31

River Reach=STEELRN         ,Main
Reach XY= 30
     1649677.662      419514.134     1649755.249      419261.679
     1649716.455        418994.9     1649583.364      418882.698
     1649517.714      418469.101     1649090.987       417470.62
     1648901.795       417236.07     1648811.078      416929.304
     1648856.437       416693.56     1648725.733      416706.093
     1648474.472      416336.064     1648460.745      416050.187
     1648156.963       415893.82     1648017.904      415540.503
     1647711.138      415522.598     1647609.679      415449.786
     1647644.294      415346.536     1646920.948      415098.259
     1646748.467      414814.172     1646470.945      414764.636
     1646140.306      414396.398     1645108.404      414245.402
     1644815.365      414019.207     1644496.066       414044.87
     1644126.037      413861.646     1643488.633      413347.784
     1643138.896      413174.109     1642993.272      412921.057
     1642850.035      412866.746     1642277.638      412203.534

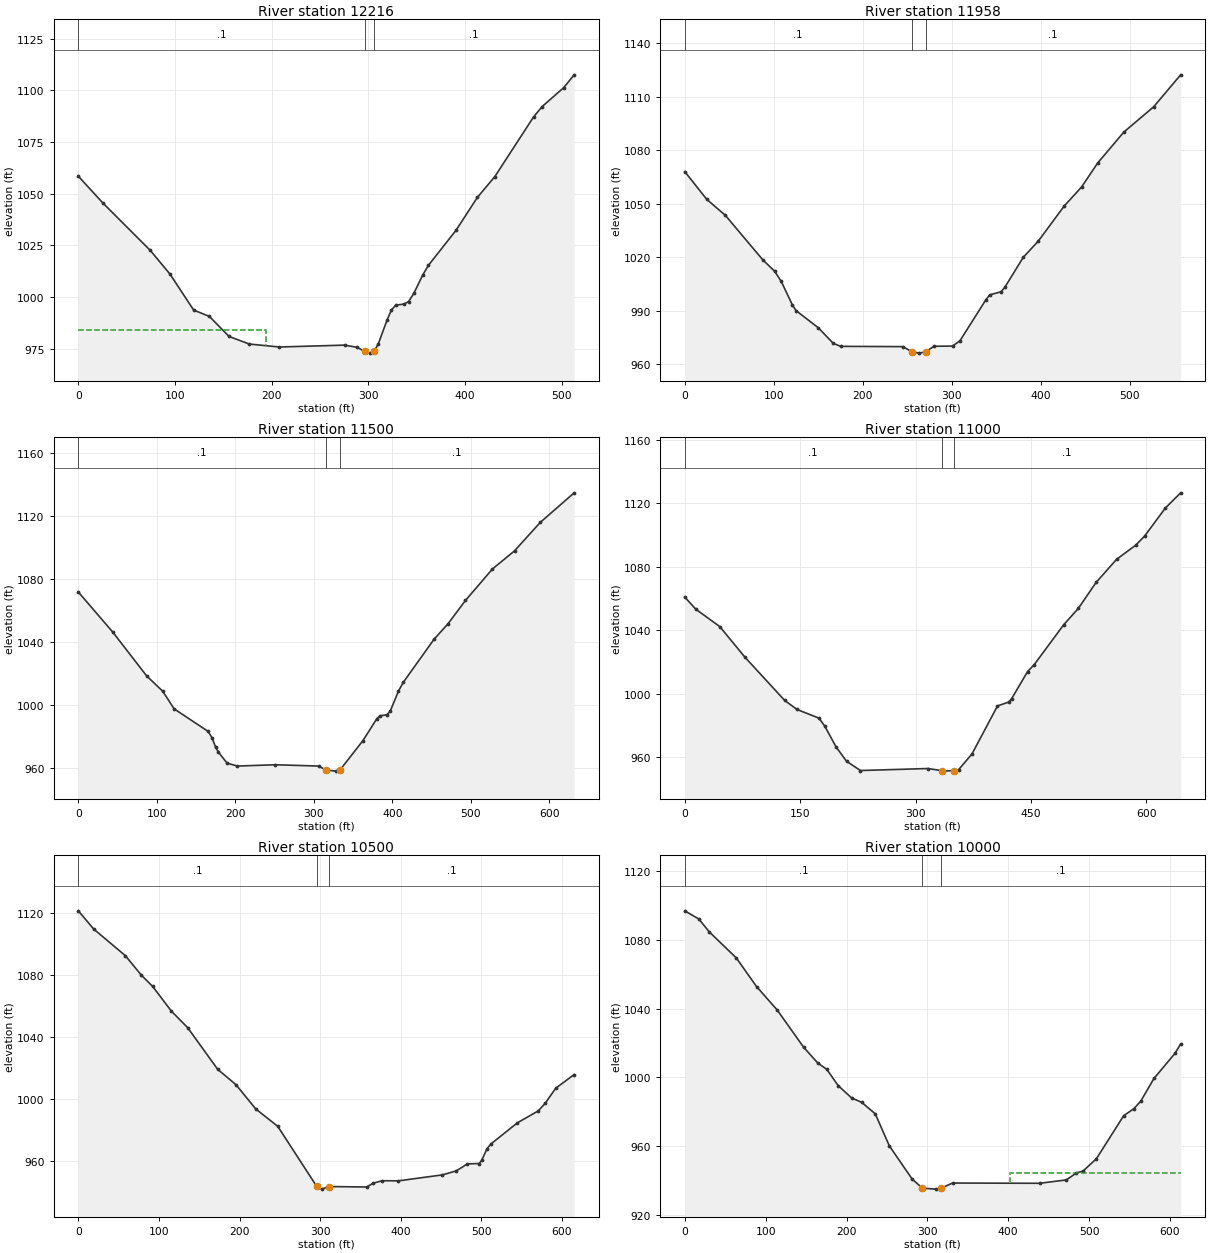
Type RM Length L Ch R = 1 ,12216   ,261.5,258,249.9
XS GIS Cut Line= 3
1649824.90826546419689.6853714591649794.33266558 419531.71143873
1649478.38480012419376.285472658
#Sta/Elev= 30
       0 1058.46    25.2  1045.6    74.5 1022.55    94.9 1011.07   119.3  993.74
   135.6  990.65     156  980.95   176.9  977.29     208  975.86   275.5  976.77
   288.2  975.73   296.4  973.75   301.6   972.9  306.03973.7529   310.5  977.54
   319.4  988.88   323.9  993.73   328.3  996.06   337.2  996.66   341.7  997.84
   347.2 1001.88   356.2 1010.56   362.1  1015.3   390.7 1032.25   412.9 1048.23
   430.9 1058.25     471 1087.13   479.9 1092.15   502.2  1101.3     513 1107.49
#Mann= 3 ,-1,0
       0      .1       0   296.4    .045       0  306.03      .1       0
#XS Ineff= 2 , 0
           194.1  984.14
Permanent Ineff=
       F       F
Bank Sta=296.4,306.03
XS Rating Curve= 0 ,0
Exp/Cntr(USF)=0,0
Exp/Cntr=0.3,0.1

Type RM Length L Ch R = 1 ,11958   ,456.6,457.7,454.9
XS GIS Cut Line= 2
1649995.62203148419166.0782234621649463.09700018419329.148089505
#Sta/Elev= 30
       0 1067.99    24.6 1052.44    45.5 1043.49    87.3 1018.65   100.9 1012.06
   108.3  1006.4   120.8  993.19     125  989.94   150.1  980.29   166.8  971.56
   175.2  969.91     245  969.76   254.7  966.96     263  966.11   270.6  966.85
   279.8  969.96   300.7  970.06     309  973.02   338.3  996.15   342.5   998.8
   355.1 1000.54   359.3 1002.95   380.2 1019.93   396.9  1028.9   426.2 1048.71
   445.6 1059.33   463.8 1072.86   493.1 1090.17   526.6 1104.35   556.9 1122.31
#Mann= 3 ,-1,0
       0      .1       0   254.7    .045       0   270.6      .1       0
Bank Sta=254.7,270.6
XS Rating Curve= 0 ,0
Exp/Cntr(USF)=0,0
Exp/Cntr=0.3,0.1

Type RM Length L Ch R = 1 ,11500   ,498.5,500,496.3
XS GIS Cut Line= 6
1649856.14208476418703.4014082551649774.12617268 418761.29105626
1649695.57285209418813.7814368461649625.42502651418851.701636583
1649532.29365109 418890.309499011649296.29543543418990.153459415
#Sta/Elev= 30
       0 1071.66    44.1  1046.1    86.9 1018.52   107.6 1008.67   122.1  997.51
   165.3  983.27   170.2  979.32     175  973.09   178.2  970.31   189.4  963.17
   202.4  961.26   251.1  962.08   306.3  961.25     315   958.8     328  958.04
  333.39958.7797   362.6   977.4   380.3  991.29   384.3  993.12     393  993.76
   397.3  995.99   407.8 1008.72   413.9  1014.3     453 1041.55   471.2 1051.64
   493.2 1066.29   527.6 1086.27   555.7 1097.75   588.4 1115.75   631.7 1134.56
#Mann= 3 ,-1,0
       0      .1       0     315    .045       0  333.39      .1       0
Bank Sta=315,333.39
XS Rating Curve= 0 ,0
Exp/Cntr(USF)=0,0
Exp/Cntr=0.3,0.1

Type RM Length L Ch R = 1 ,11000   ,500,500,499.6
XS GIS Cut Line= 6
1649745.13410467418265.5282682631649655.51912643418307.958957672
1649569.77520342418350.2708809231649493.76124784418390.590026006
1649403.39988001418448.6128758341649188.76152976418588.592910841
#Sta/Elev= 30
       0 1060.81    14.4 1053.16    45.4 1042.28    78.1 1023.01   129.7  995.82
   145.7  990.09   174.3  984.62   181.8  979.66   196.6   966.5   210.2  957.45
   228.3  951.61     316  952.87  333.83951.5479   336.2  951.23   349.3  951.54
   355.8  952.11   373.2  962.03   406.4  992.28   420.8   994.7   424.7  996.79
   445.4 1013.87     454 1018.22   492.4  1043.4   511.5 1053.72   534.5 1070.04
   561.1 1084.58   585.8 1093.42   597.5 1099.19   624.6 1116.94   644.4 1126.49
#Mann= 3 ,-1,0
       0      .1       0  333.83    .045       0   349.3      .1       0
Bank Sta=333.83,349.3
XS Rating Curve= 0 ,0
Exp/Cntr(USF)=0,0
Exp/Cntr=0.3,0.1

Type RM Length L Ch R = 1 ,10500   ,494.5,500.7,501
XS GIS Cut Line= 6
1649547.62400101417815.0439330041649338.75532426417963.408465669
1649255.99597535418019.5464767521649194.68966751418062.795405999
1649122.40700367418112.2834960071649087.93440469418202.300432208
#Sta/Elev= 30
       0 1121.67      19 1109.93    58.2 1092.78    78.2 1080.12    92.3  1072.8
   115.5 1056.86   135.6 1046.26   172.9 1019.32   195.6 1009.39   220.1  993.75
   247.4   982.5  295.86943.6356   302.1  941.93   310.8   943.6   357.9  943.31
   365.8  945.78   376.9  947.36     397  947.27   451.6  951.12   468.9  953.71
   482.8  958.23   497.4  958.46   500.5  960.53   507.1  968.08     512  971.13
   544.8  984.77   570.5  992.39   579.1  997.25   592.3 1007.08   615.2 1015.93
#Mann= 3 ,-1,0
       0      .1       0  295.86    .045       0   310.8      .1       0
Bank Sta=295.86,310.8
XS Rating Curve= 0 ,0
Exp/Cntr(USF)=0,0
Exp/Cntr=0.3,0.1

Type RM Length L Ch R = 1 ,10000   ,502,500.6,498.9
XS GIS Cut Line= 6
1649416.82669042417464.5577573331649243.88117017417519.531728759
 1649172.1368911417541.5953329211649075.61608675417567.751776665
1648918.50550859 417609.254646421648829.39807525417639.637459666
#Sta/Elev= 30
       0 1097.06    17.5 1092.23    30.1 1084.88    63.7 1069.62    88.9 1052.84
   114.1  1039.4     147 1017.59   164.4 1008.42   175.7 1004.68   189.6  995.29
   206.3  988.05   218.9  985.49   235.6  978.77   252.9  960.19   281.4  940.67
   293.9  935.51   310.4  934.95  317.04935.4984   331.2   938.5   438.8  938.35
   471.9  940.32   484.3  944.36   492.5  945.47   509.1  952.69   542.7  977.67
   555.4  981.83   563.8  986.12   580.2   999.4   606.1 1013.96   613.2 1019.49
#Mann= 3 ,-1,0
       0      .1       0   293.9    .045       0  317.04      .1       0
#XS Ineff= 2 , 0
                          401.58           944.5
Permanent Ineff=
       F       F
Bank Sta=293.9,317.04
XS Rating Curve= 0 ,0
Exp/Cntr(USF)=0,0
Exp/Cntr=0.3,0.1

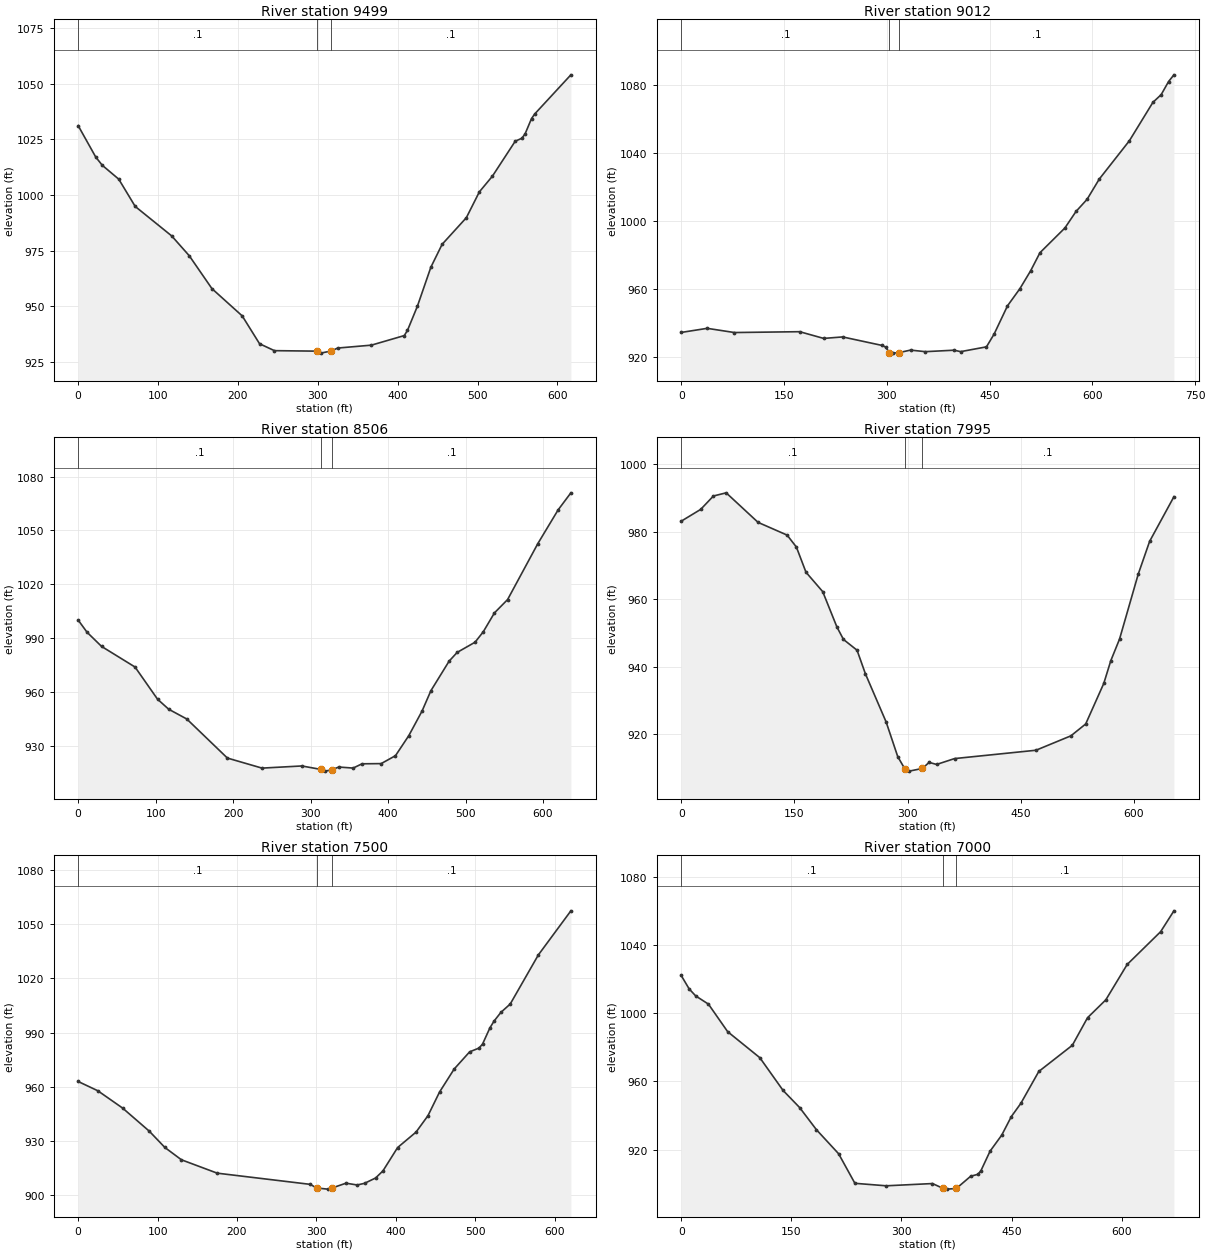
Type RM Length L Ch R = 1 ,9499    ,485.6,486.8,480.6
XS GIS Cut Line= 6
1649181.48168868417039.654407665 1649090.1350866417061.963418171
1649006.66281259417088.5063440951648842.03846993417148.524596751
   1648768.08619417166.2962147591648587.80866343417203.178686917
#Sta/Elev= 30
       0 1031.09      22 1016.98    30.2 1013.28    50.8 1007.06    71.4  994.81
   117.1  981.57   139.1  972.66   167.5  957.89   205.4  945.65   227.1  933.15
   245.7  930.05   298.9  929.83   303.7  928.94  316.88929.9106   324.9  931.22
   367.1  932.52   408.3  936.82   412.3  939.15   424.7  949.98   441.6  967.53
   455.7  977.81     486  989.75   502.3 1001.35   518.7 1008.43   547.2  1024.1
   555.4 1025.41   559.5 1027.34   567.6 1034.26   571.7 1036.37   616.9 1053.91
#Mann= 3 ,-1,0
       0      .1       0   298.9    .045       0  316.88      .1       0
Bank Sta=298.9,316.88
XS Rating Curve= 0 ,0
Exp/Cntr(USF)=0,0
Exp/Cntr=0.3,0.1

Type RM Length L Ch R = 1 ,9012    ,505.4,505.7,496.3
XS GIS Cut Line= 6
1649125.65240401416547.1950907561648896.45404351416661.791318253
1648789.72722284416752.2678433361648701.31926318416814.075790584
 1648606.1987185416865.7551491711648509.04766609416910.033275843
#Sta/Elev= 30
       0   934.5    37.9  936.91    77.7  934.44   172.9  934.94   207.9  930.99
   235.6  931.86   293.4  926.84   298.2   925.9   303.9  922.68   309.1  922.34
     318  922.65   334.7  924.12   356.3   923.2   398.1  924.06   407.9  923.22
   445.5  926.03   456.7  933.57   476.2  950.14   494.4  960.29     510  970.76
   523.6  981.37     560   995.9   576.2 1005.61   592.3 1012.71   610.1 1024.61
   654.1 1047.17   688.4 1069.72   700.5 1074.27   711.3 1081.97   719.1 1085.91
#Mann= 3 ,-1,0
       0      .1       0   303.9    .045       0     318      .1       0
Bank Sta=303.9,318
XS Rating Curve= 0 ,0
Exp/Cntr(USF)=0,0
Exp/Cntr=0.3,0.1

Type RM Length L Ch R = 1 ,8506    ,513.2,510.9,503.7
XS GIS Cut Line= 6
1648805.30396333 416221.884061591648721.43602084416277.360328585
  1648654.476181416340.499309927 1648570.0317961416495.861860082
1648524.14376451416558.7531385121648388.03150393416687.680046007
#Sta/Elev= 30
       0 1000.01    11.4  993.26    30.2  985.34    73.4  973.85   102.4  955.95
   116.8  950.35   140.2  944.89   192.6  923.12   237.3  917.52   288.7  918.72
  313.84916.7518   319.1  915.84   327.8  916.69   336.5  918.12   354.9  917.54
   366.4  919.92   391.1  920.03   409.6  924.45   426.8  935.64   443.9  949.33
   455.3  960.66   478.8  977.12   489.2     982   512.3  987.68   522.9  993.49
   537.3 1004.01   554.3 1011.45   593.3 1042.61   619.5 1061.41     636 1070.93
#Mann= 3 ,-1,0
       0      .1       0  313.84    .045       0   327.8      .1       0
Bank Sta=313.84,327.8
XS Rating Curve= 0 ,0
Exp/Cntr(USF)=0,0
Exp/Cntr=0.3,0.1

Type RM Length L Ch R = 1 ,7995    ,489.5,495.6,502.3
XS GIS Cut Line= 6
1648522.14901784415736.1655448381648438.73514268415978.459351584
1648397.84710109416070.1428952521648342.12772433416131.948874012
1648258.41529334416193.0484893321648164.65301368416249.949622259
#Sta/Elev= 30
       0  983.08    25.8  986.58    42.7  990.55    59.6  991.49   101.9  982.73
   140.4  978.96   152.7  975.41   165.4  967.96   187.6   962.2   206.4  951.73
   215.1  948.03   233.1  944.84   244.2  937.84   271.7  923.55   287.1  913.27
   296.2  909.77   302.3     909   319.8   909.8   328.6  911.59   338.6  910.98
   362.4  912.72   470.3  915.19   516.6  919.46   536.2  922.97   560.2     935
   569.6  941.79   581.1  948.14   605.9   967.4     621  977.12   653.2  990.34
#Mann= 3 ,-1,0
       0      .1       0   296.2    .045       0   319.8      .1       0
Bank Sta=296.2,319.8
XS Rating Curve= 0 ,0
Exp/Cntr(USF)=0,0
Exp/Cntr=0.3,0.1

Type RM Length L Ch R = 1 ,7500    ,503.9,500,488.5
XS GIS Cut Line= 6
1648349.98597634415569.8450113391648263.48614934415608.195984513
  1648185.772394415648.7510215041647970.28890109415775.505689248
1647895.00361858415820.098119751 1647820.8187276415888.289912507
#Sta/Elev= 30
       0  962.87    24.7  957.74      56  948.12    89.6  935.31   109.2  926.29
     130  919.47   175.1  912.05   292.3  905.84   300.3  903.84   314.1   903.2
   319.4903.7932   337.3  906.49   351.3   905.5   360.6  906.41   374.5  909.36
   383.8   913.3   402.3  926.26   425.5  934.82   440.5  943.91   455.1  957.03
   473.5  969.78     493  979.32   504.7  981.38   509.2  983.57   518.5  992.59
   523.7  996.33   532.3 1001.17   544.1 1005.82   579.5 1033.03   620.5 1057.49
#Mann= 3 ,-1,0
       0      .1       0   300.3    .045       0   319.4      .1       0
Bank Sta=300.3,319.4
XS Rating Curve= 0 ,0
Exp/Cntr(USF)=0,0
Exp/Cntr=0.3,0.1

Type RM Length L Ch R = 1 ,7000    ,498.2,500,499
XS GIS Cut Line= 6
1647918.07935984415219.6199900061647859.30519918415317.680161342
1647796.16129659415410.931615248  1647739.970136415478.713631928
1647713.20575383415575.0654733331647644.62321384415821.967210501
#Sta/Elev= 30
       0 1022.11    10.8 1014.26    19.7 1010.15    37.1 1005.32    63.3  989.16
   107.1  973.92   138.8  954.71   161.3  944.71   184.2  931.71   214.4  917.63
   236.6  900.29   279.3  898.83   342.3  900.15  356.88897.2848   362.5  896.88
   374.8  897.27   394.3  904.43   404.1  905.56   408.2   907.6   420.7  919.11
   436.6  928.52   449.7  939.41   462.6  947.12   487.1  965.85   532.8   981.2
   553.5  997.35   578.4 1007.83   607.5 1028.57   653.1 1047.79   671.2 1060.02
#Mann= 3 ,-1,0
       0      .1       0  356.88    .045       0   374.8      .1       0
Bank Sta=356.88,374.8
XS Rating Curve= 0 ,0
Exp/Cntr(USF)=0,0
Exp/Cntr=0.3,0.1

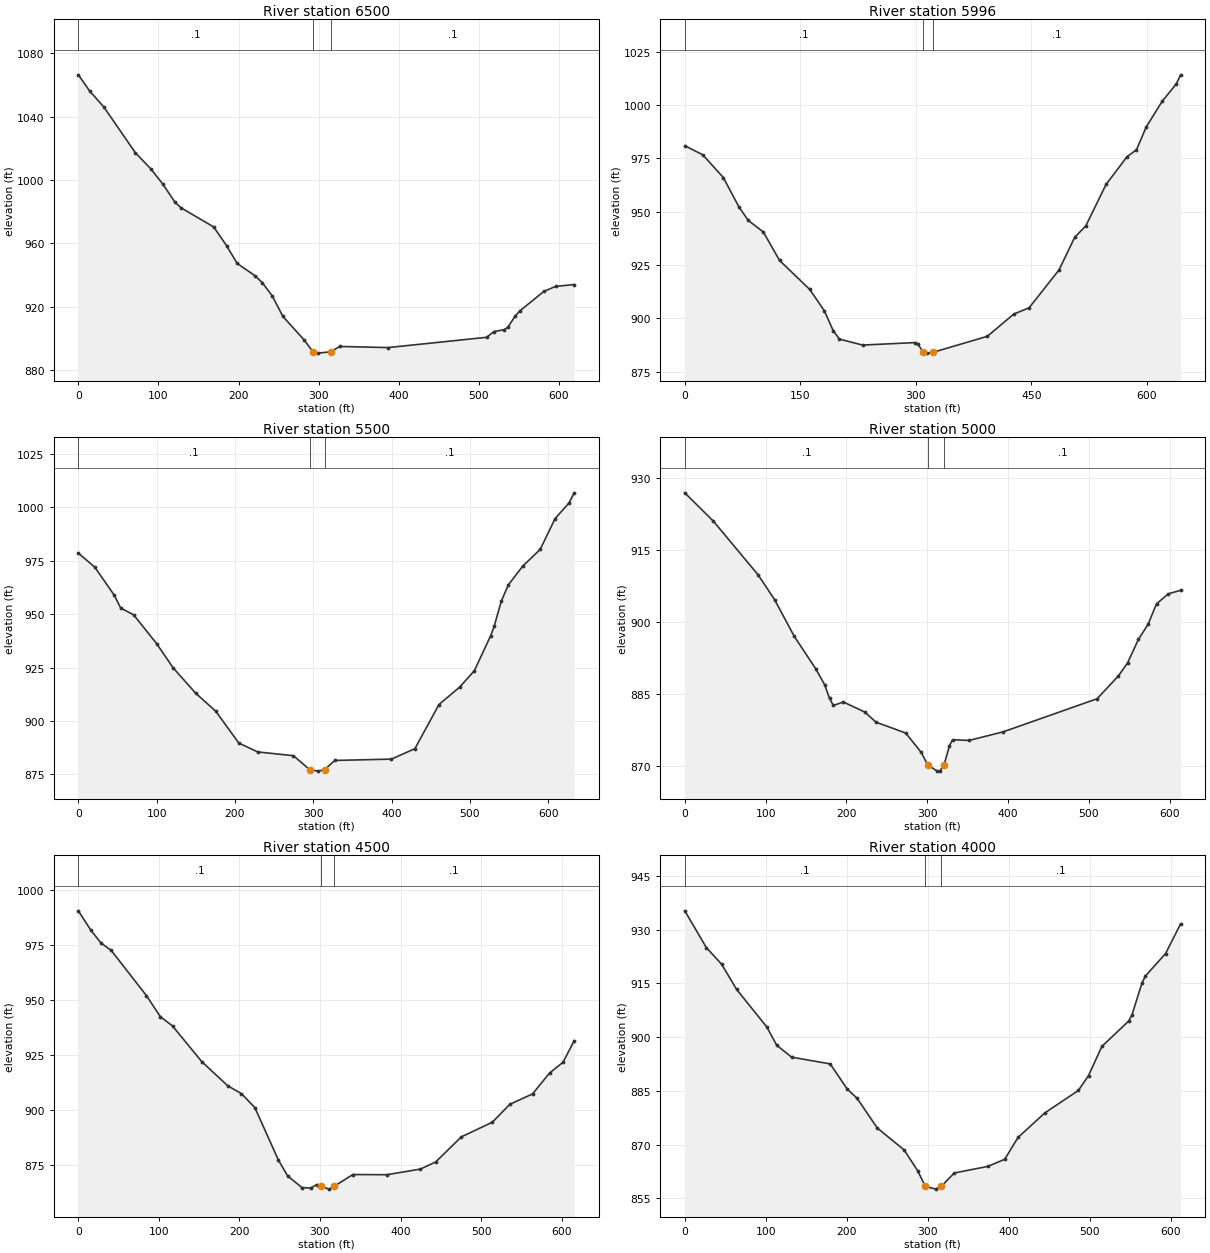
Type RM Length L Ch R = 1 ,6500    ,505.1,503.9,500.1
XS GIS Cut Line= 6
1647550.59453051414983.5640316751647445.63542284415217.332593009
1647404.67520292415308.5587885081647375.91443367415377.865408421
  1647347.778007415461.9836785051647302.48052542415550.192491591
#Sta/Elev= 30
       0 1066.47    14.2 1056.22    31.8 1046.19    71.2 1017.28    90.4 1007.12
   105.5  997.47   120.6  986.05   128.2  982.48     169   970.4   185.2  958.47
   198.4  947.31   220.3   939.7   229.6  935.26   242.2   926.8   255.4   913.9
   281.7  899.15   293.1  891.51     299  890.69  314.87891.5096   326.4  894.91
   386.5  894.19     510  900.69   518.6  904.27   531.9  905.53   536.3  907.04
   545.3  913.99   551.3  917.39   581.3  929.67   595.9  932.83   619.1     934
#Mann= 3 ,-1,0
       0      .1       0   293.1    .045       0  314.87      .1       0
Bank Sta=293.1,314.87
XS Rating Curve= 0 ,0
Exp/Cntr(USF)=0,0
Exp/Cntr=0.3,0.1

Type RM Length L Ch R = 1 ,5996    ,491.9,496.1,494.1
XS GIS Cut Line= 6
1647089.11317001414804.2182617491647033.45219208414887.317505002
 1646997.5861221414970.8829546721646981.84632418415046.197764665
 1646989.2413225415146.1276829241646885.36685833415401.426384926
#Sta/Elev= 30
       0  980.93    23.4  976.68      50  966.02    70.1  952.37    82.2  945.97
     102  940.46   123.1  927.11   162.3  913.51   181.2  903.52   192.6  894.26
   200.8  890.24   230.8  887.44   298.3  888.59   302.3  888.12   309.5  884.13
   314.4  883.66   322.4  884.06   392.8  891.54   427.2  901.98   447.1  904.93
   485.9  922.69   506.3  937.99   520.7  943.36     547  962.79   574.3  975.82
   586.5  979.06   599.2  989.79   619.8 1001.75   638.1 1009.92   643.8  1014.2
#Mann= 3 ,-1,0
       0      .1       0   309.5    .045       0   322.4      .1       0
Bank Sta=309.5,322.4
XS Rating Curve= 0 ,0
Exp/Cntr(USF)=0,0
Exp/Cntr=0.3,0.1

Type RM Length L Ch R = 1 ,5500    ,495.3,500,502.5
XS GIS Cut Line= 6
 1646753.8520295414500.3691319231646728.74545242414590.855827585
 1646645.8092666414839.9156969191646618.49075167414911.170475677
1646578.63486026414998.3474666771646529.74322575415090.891572922
#Sta/Elev= 30
       0  978.55      21  971.98    45.8  958.91    54.1  952.86    70.7  949.65
    99.9  936.24   121.2  924.82   149.9     913   175.4  904.61     205  889.67
     229  885.52   274.8  883.74  295.43877.2411   306.4  876.53   314.8  877.28
   327.5  881.53   399.9  882.15   429.9  887.03   460.6  907.69     487  915.83
   505.8  923.48   526.6  939.85   531.1  944.23   540.1  955.91   549.2  963.66
   567.6  972.45   589.9  980.29     609  994.74   626.8 1002.04   633.3 1006.76
#Mann= 3 ,-1,0
       0      .1       0  295.43    .045       0   314.8      .1       0
Bank Sta=295.43,314.8
XS Rating Curve= 0 ,0
Exp/Cntr(USF)=0,0
Exp/Cntr=0.3,0.1

Type RM Length L Ch R = 1 ,5000    ,502.1,500,494.1
XS GIS Cut Line= 6
1646484.30860534414315.5289504231646417.22179726414382.541283593
1646358.36200684414447.3397104291646309.63802293 414504.35665676
1646139.10457134414703.9176093341646078.19950943414775.189448416
#Sta/Elev= 30
       0  926.85    35.4  920.94    90.7  909.76   111.2  904.56   135.3  896.98
   161.9   890.2   173.2  886.81   179.1  883.99   183.9  882.52   196.2  883.25
   222.8  881.14   236.6  879.04   273.4  876.77   292.6  872.74  300.69870.1042
   312.5  868.83   315.5  868.86   320.7  870.03   327.4  874.06   331.3  875.37
   352.1  875.24   394.4  877.04   510.2  883.92   536.5  888.66     548  891.41
   561.4   896.3   573.3  899.44   583.8  903.71   598.4   905.8   613.6  906.53
#Mann= 3 ,-1,0
       0      .1       0  300.69    .045       0   320.7      .1       0
Bank Sta=300.69,320.7
XS Rating Curve= 0 ,0
Exp/Cntr(USF)=0,0
Exp/Cntr=0.3,0.1

Type RM Length L Ch R = 1 ,4500    ,500.2,500,499.7
XS GIS Cut Line= 6
1645913.20508876414076.4579062611645902.22512384414171.476417005
1645888.22154292414258.9700084181645867.47781801414331.097488835
1645836.31186984414426.1166557521645756.44785634414669.603701591
#Sta/Elev= 30
       0  990.57    15.5  981.78    28.3  975.87    40.8  972.58    84.6  951.98
   101.9   942.4     117  938.17   153.4   921.9   185.6  910.94   202.5   907.4
   219.2  901.02   248.3  877.24   259.9  869.94   277.7  864.65   288.5  864.44
   295.8  866.01  301.52865.1913   311.3  863.95  317.62865.2269   340.8  870.59
   382.9  870.51   424.8  873.07   443.8  876.35   475.5  887.72     514  894.39
   535.7  902.53   563.9  907.26     585  916.75   601.8  921.68   615.6  931.45
#Mann= 3 ,-1,0
       0      .1       0  301.52    .045       0  317.62      .1       0
Bank Sta=301.52,317.62
XS Rating Curve= 0 ,0
Exp/Cntr(USF)=0,0
Exp/Cntr=0.3,0.1

Type RM Length L Ch R = 1 ,4000    ,501.7,504.2,505.3
XS GIS Cut Line= 6
1645442.22998084413994.8012454211645395.40133435414169.897351921
1645376.02374843414242.3509471711645350.18718593414338.955740839
1645308.20334601414495.9383665031645283.98160967 414586.50544259
#Sta/Elev= 30
       0  935.26    26.6     925    45.6  920.33    63.9  913.36   101.2  902.87
   113.6  897.73     132  894.41   179.6  892.54   200.5  885.56     213  882.89
   237.8  874.63   270.9  868.53   287.5  862.77   297.2  858.34   310.2  857.58
   316.8  858.37     333  862.09   374.4  863.93   395.2  865.91   411.7  872.02
   444.8  878.86   486.2  885.13   498.7  889.25   515.2  897.41   548.4  904.51
   552.5  906.29   564.9  915.21   569.1  917.09   593.9  923.33   612.5  931.64
#Mann= 3 ,-1,0
       0      .1       0   297.2    .045       0   316.8      .1       0
Bank Sta=297.2,316.8
XS Rating Curve= 0 ,0
Exp/Cntr(USF)=0,0
Exp/Cntr=0.3,0.1

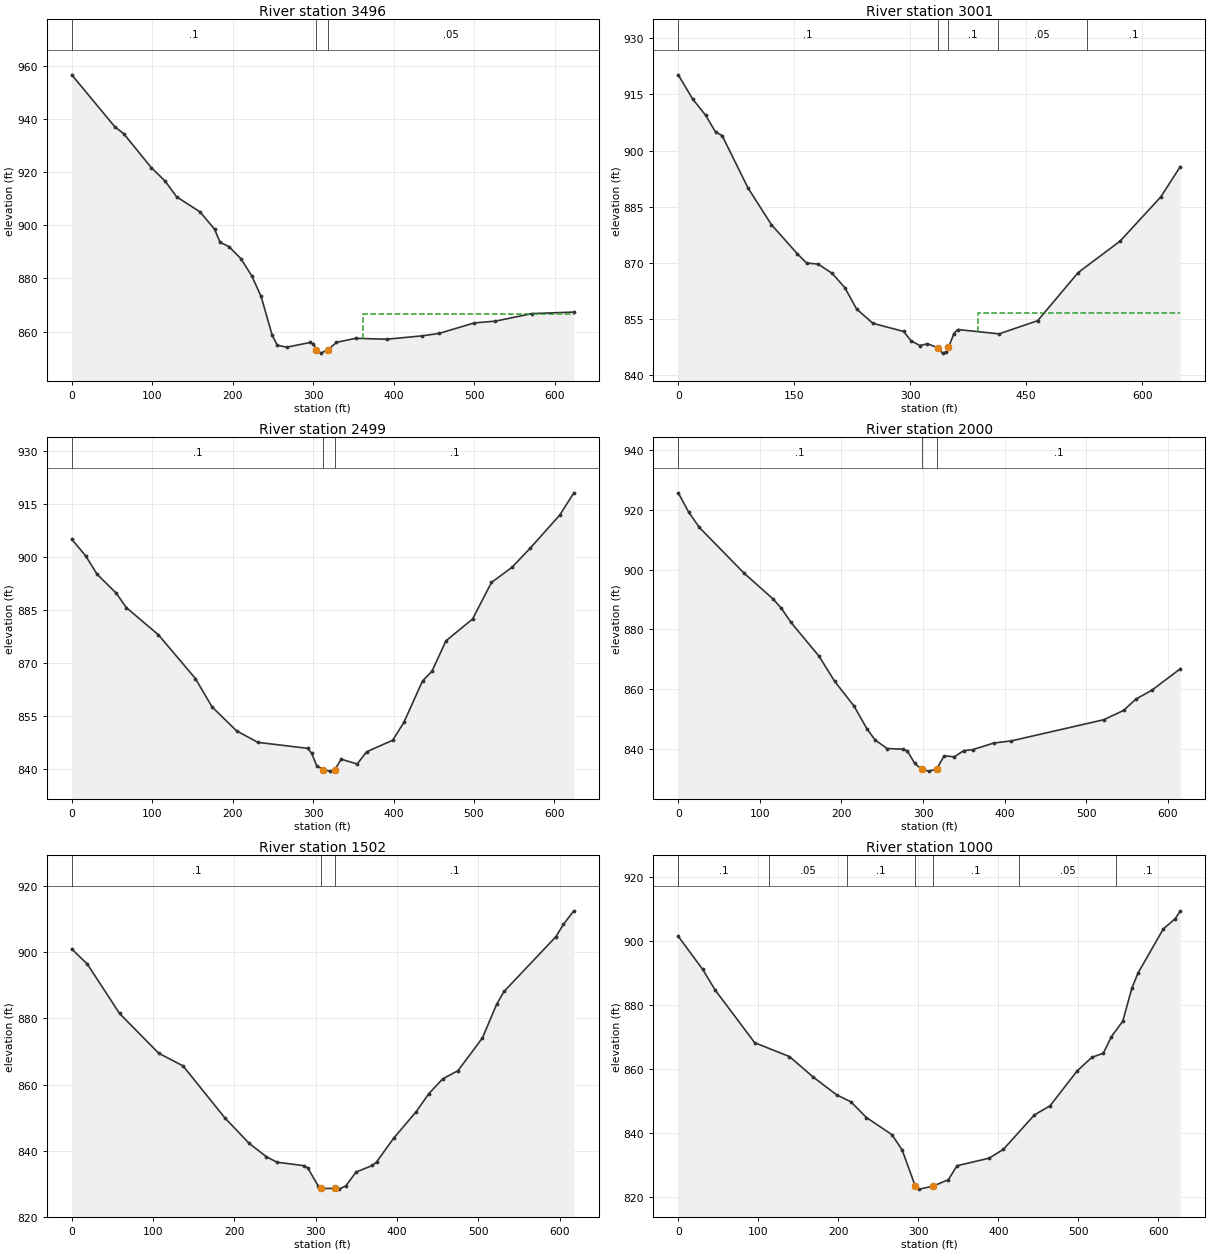
Type RM Length L Ch R = 1 ,3496    ,493.1,495,494.5
XS GIS Cut Line= 6
1645105.44554943413874.2906596661644979.20990951414008.932450756
1644933.91964576 414070.091777251644885.93122467414158.072244346
 1644774.0334826414279.5969356751644718.20091709414359.354322091
#Sta/Elev= 30
       0   956.8    53.4  937.23    64.5  934.61    98.7  921.82   115.7  916.82
   130.2   910.8   159.3  905.11   177.3  898.61   184.1  893.67   195.1  892.05
     210  887.48   223.4  881.04   235.1  873.26   248.8  858.68   255.2  854.85
   266.8  854.08   296.3  855.88   299.9  855.29  303.85 853.178   309.1  851.85
   318.2   853.1   328.7   855.9   352.5  857.44   391.1  857.09   434.8  858.36
   455.9  859.26   499.8  863.24   526.1  863.91   571.2  866.75   623.5  867.33
#Mann= 3 ,-1,0
       0      .1       0  303.85    .045       0   318.2     .05       0
#XS Ineff= 2 , 0
                          362.17          866.56
Permanent Ineff=
       F       F
Bank Sta=303.85,318.2
XS Rating Curve= 0 ,0
Exp/Cntr(USF)=0,0
Exp/Cntr=0.3,0.1

Type RM Length L Ch R = 1 ,3001    ,499.8,501.4,502.4
XS GIS Cut Line= 6
 1644615.5101776413726.7437106671644582.67559759413826.100795418
1644542.18978618413916.6898530871644497.15247467413989.825205505
1644437.82746209414074.4513485881644293.94290733   414286.491935
#Sta/Elev= 30
       0   920.2    18.7  913.74    35.6  909.38    48.2  904.95    56.7  904.01
    90.4  889.96   120.5  880.23   153.8  872.51     166  869.98   181.1   869.7
   199.3   867.2   215.5  863.42   230.7  857.72   251.8   853.9   291.6  851.73
   301.1  849.24   312.6  847.97   322.4  848.46   335.5   847.4   341.9  845.95
   346.8  846.35  349.52847.4521   356.6  851.18   361.5  852.25     415  851.09
     465  854.62   517.3  867.45   571.5  875.83   624.1  887.62   649.4  895.72
#Mann= 5 ,-1,0
       0      .1       0   335.5    .045       0  349.52      .1       0
  413.11     .05       0  528.11      .1       0
#XS Ineff= 2 , 0
                          387.49          856.64
Permanent Ineff=
       F       F
Bank Sta=335.5,349.52
XS Rating Curve= 0 ,0
Exp/Cntr(USF)=0,0
Exp/Cntr=0.3,0.1

Type RM Length L Ch R = 1 ,2499    ,498.6,499.3,496.7
XS GIS Cut Line= 6
1644254.94889084413561.8441060931644202.28364184413645.553584337
1644145.05770643413717.0885462611644090.46660826413771.470655337
1644018.64391726413841.5508957511643832.86312084414018.043324918
#Sta/Elev= 30
       0  904.94    17.4  900.19    31.5  895.03    55.2   889.7    67.8   885.6
   107.8  877.87   153.8  865.49   174.4  857.49   204.9  850.71   231.4  847.45
   293.2  845.76   298.3  844.36   304.4  840.89   312.4  839.71   321.1  839.31
  327.01839.7343     335   842.7   354.8  841.31   366.5  844.77     399  848.06
   412.9   853.1   436.1  864.85   447.7  867.52   465.2  876.19   498.3  882.36
   521.8  892.71   547.2  896.97   569.9   902.4   606.6  911.75   624.2  918.07
#Mann= 3 ,-1,0
       0      .1       0   312.4    .045       0  327.01      .1       0
Bank Sta=312.4,327.01
XS Rating Curve= 0 ,0
Exp/Cntr(USF)=0,0
Exp/Cntr=0.3,0.1

Type RM Length L Ch R = 1 ,2000    ,499.3,498.3,493.6
XS GIS Cut Line= 6
1643848.70298417413294.684207335 1643787.7972661413367.560373917
1643733.90629776413437.7908765081643689.59667508413499.120478258
1643629.59548275413579.1196620911643475.84546217413784.119580179
#Sta/Elev= 30
       0  925.78    12.8  919.32    25.9  914.17    80.6  898.89   116.4  890.18
   126.5  887.07   138.2  882.37   172.5  871.08   191.8  862.61   215.4  854.38
   231.3  846.73   241.2  843.01     256  840.12   275.5  839.89   280.9  839.29
   289.8  835.16   298.4  833.17   306.9  832.55   316.7833.2004   325.9  837.66
   338.4  837.35   349.8   839.4   360.9  839.74   386.9  841.97   408.3  842.68
   521.7  849.78   545.9   852.9   560.9  856.66   580.9  859.73   615.4  866.84
#Mann= 3 ,-1,0
       0      .1       0   298.4    .045       0   316.7      .1       0
Bank Sta=298.4,316.7
XS Rating Curve= 0 ,0
Exp/Cntr(USF)=0,0
Exp/Cntr=0.3,0.1

Type RM Length L Ch R = 1 ,1502    ,503.3,501.6,501
XS GIS Cut Line= 6
 1643396.9161581412951.170458674  1643357.305673413036.349094093
1643300.09154859413188.3583045011643243.83017817413354.668011263
1643204.99167317413435.3604351731643159.23192218413519.860266179
#Sta/Elev= 30
       0  901.03    19.2  896.44    58.8  881.51     107  869.48   136.9  865.66
   188.2  849.97   218.1  842.25   239.5  838.17   252.3  836.54   286.2  835.45
   290.4  834.77   303.2   829.3  306.37828.5878   324.3  828.58   328.6  828.38
     337  829.34   349.8  833.55   369.7  835.53     375  836.63   396.1  843.83
   423.7  851.82   439.1  857.24   456.2  861.71   475.1  864.23   505.1   874.1
   522.8  884.37   531.7  888.17   595.6  904.77   604.7  908.46   617.6  912.57
#Mann= 3 ,-1,0
       0      .1       0  306.37    .045       0   324.3      .1       0
Bank Sta=306.37,324.3
XS Rating Curve= 0 ,0
Exp/Cntr(USF)=0,0
Exp/Cntr=0.3,0.1

Type RM Length L Ch R = 1 ,1000    ,497,501.5,505.4
XS GIS Cut Line= 6
1643062.14812684412611.0599184191643028.42312868412698.535137177
1642935.32784243412943.9726384281642899.36794059 413013.36816892
1642852.89985767413092.8516057581642792.50266875413173.524016589
#Sta/Elev= 30
       0  901.37    30.6  891.01      46  884.62    95.5   868.1     139  863.76
   168.6  857.37   197.9   851.8   215.7  849.63   235.1  844.71     267  839.35
   279.8  834.55  295.99823.3556   301.2  822.32   318.4  823.26   337.5  825.27
   348.3  829.63   388.4     832   406.2  834.74     445  845.52   464.6  848.38
   498.3  859.25   516.8  863.52   531.1  864.81   541.1  869.95   555.4  874.83
   566.8  885.17   574.5   889.9     606  903.65   621.1  906.91   627.3  909.33
#Mann= 7 ,-1,0
       0      .1       0  113.75     .05       0  211.25      .1       0
  295.99    .045       0   318.4      .1       0  426.25     .05       0
  546.48      .1       0
Bank Sta=295.99,318.4
XS Rating Curve= 0 ,0
Exp/Cntr(USF)=0,0
Exp/Cntr=0.3,0.1

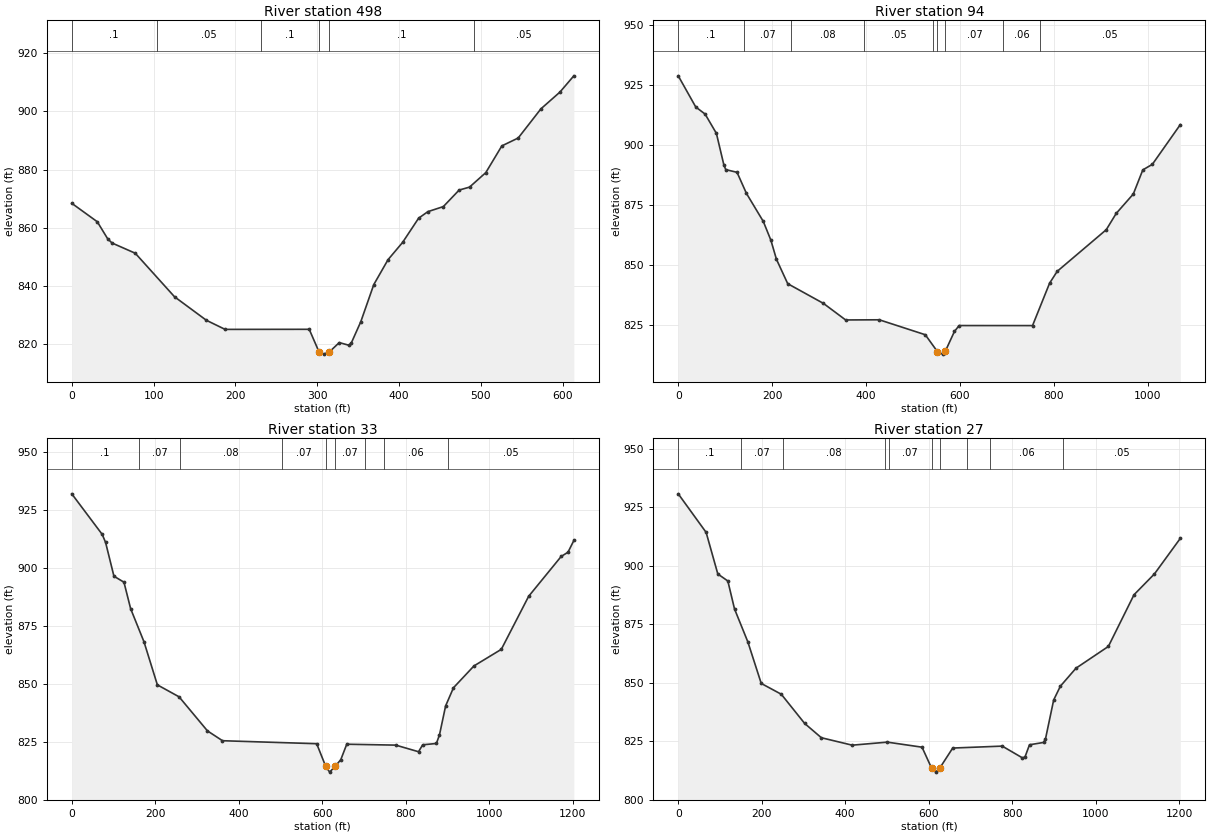
Type RM Length L Ch R = 1 ,498     ,405.3,404.2,402.5
XS GIS Cut Line= 6
1642783.75104584412339.0342157481642622.30254984412538.028240338
1642556.91226067412613.7482332591642505.07771868412668.273386672
1642444.30782709412731.6584305021642381.22724459412801.686505675
#Sta/Elev= 30
       0  868.42    31.2  862.08    43.9  856.23    49.2  854.79    77.6  851.28
   125.6  836.33   164.5  828.27   187.4  825.14   290.2  825.17  302.23817.3853
   307.8  816.65   314.7  817.38   326.9  820.61   338.8  819.69   341.8  820.59
   353.2  827.76   369.1  840.52   386.5  849.06   404.3  854.99   423.9  863.31
   435.2  865.55   454.1  867.29   473.4  872.96   486.1  873.97     506  878.95
   525.6  888.12   545.6  890.83   573.4  900.85   596.6  906.59   613.6  912.17
#Mann= 6 ,-1,0
       0      .1       0  103.75     .05       0  231.25      .1       0
  302.23    .045       0   314.7      .1       0  491.53     .05       0
Bank Sta=302.23,314.7
XS Rating Curve= 0 ,0
Exp/Cntr(USF)=0,0
Exp/Cntr=0.3,0.1

Type RM Length L Ch R = 1 ,94      ,62.3,61.6,60.6
BEGIN DESCRIPTION:
Structure 1 XS 4
END DESCRIPTION:
XS GIS Cut Line= 6
1642785.40035499412078.4213169381642428.81242135412086.447411908
 1642364.6036616412238.943216324 1642310.7141668412312.324656044
1642202.93517721412396.0253607231642254.53150202412711.336234517
#Sta/Elev= 30
       0  928.77    37.3   915.8    57.3  912.83    81.3  904.81    97.3  891.62
   101.3  889.71   125.3  888.59   145.3  879.82   181.3  868.12   197.3  860.38
   209.3  852.37   233.3  842.21   309.4  834.01   356.7  827.11   428.4  827.18
   526.5  820.95   552.2  813.95   563.5  812.88  568.97814.0033   588.6  822.33
   598.6  824.78     755  824.76   791.4  842.44   807.6  847.36   912.1  864.69
   933.3  871.47   969.8  879.57     990   889.6  1010.3  891.91  1069.9  908.45
#Mann= 9 ,-1,0
       0      .1       0     140     .07       0     240     .08       0
  396.68     .05       0  542.14     .07       0   552.2    .045       0
  568.97     .07       0  692.93     .06       0  770.38     .05       0
Bank Sta=552.2,568.97
XS Rating Curve= 0 ,0
Exp/Cntr(USF)=0,0
Exp/Cntr=0.3,0.1

Type RM Length L Ch R = 1 ,33      ,5.9,5.8,6.4
BEGIN DESCRIPTION:
Structure 1 XS 3
END DESCRIPTION:
XS GIS Cut Line= 6
1642805.10847135412039.4374270881642390.04470294412039.437427088
1642274.23961838412267.6078412151642236.40231352412307.738316061
1642144.67551388412354.7483008811642223.78987857412718.215744491
#Sta/Elev= 30
       0  932.07      73  914.54      81  911.09     101  896.53     125  893.94
     141  882.51     173  868.21     205  849.65     257  844.49     325  829.79
     361  825.55   586.6  824.26  608.17814.4843   617.7     812  630.86814.5378
   644.2  817.33   658.6  824.04     776  823.65   830.5   820.8   840.5  823.79
   873.3  824.36   880.7  828.08   895.4  840.57   914.2   848.4   963.3  857.82
  1028.8  864.98  1094.3  887.87  1172.1  905.04  1188.5  906.88  1202.5  911.94
#Mann= 9 ,-1,0
       0      .1       0     160     .07       0     260     .08       0
  504.11     .07       0  608.17    .045       0  630.86     .07       0
  701.85     .05       0     747     .06       0  900.49     .05       0
Bank Sta=608.17,630.86
XS Rating Curve= 0 ,0
Exp/Cntr(USF)=0,0
Exp/Cntr=0.3,0.1

Type RM Length L Ch R = 1 ,27      ,,,
BEGIN DESCRIPTION:
Structure 1 XS 3
END DESCRIPTION:
XS GIS Cut Line= 6
  1642798.869531412038.0998864191642383.80576259412038.099886419
1642268.00067803412266.2703005461642230.16337317412306.400775392
1642138.43657353412353.4107602121642217.55093822412716.878203822
#Sta/Elev= 30
       0  930.75    66.8  914.27    94.8  896.49   118.8  893.49   134.8  881.54
   166.8  867.43   198.8  849.71   246.8  845.09   302.8  832.61   342.8   826.5
   416.7  823.32   500.8  824.62   583.9  822.46     607  813.43   616.9   811.8
  625.84813.3912   657.4  822.09     776  822.92   824.4  817.89   830.5  818.28
   841.3  823.49   874.9  824.48   879.5  825.91   899.2  842.64   915.2  848.52
   952.7  856.23  1030.2  865.52  1091.6  887.61  1140.5  896.51  1202.5  911.71
#Mann= 10 ,-1,0
       0      .1       0     150     .07       0     250     .08       0
  494.11     .05       0  504.11     .07       0     607    .045       0
  625.84     .07       0  691.85     .05       0  747.01     .06       0
   920.5     .05       0
Bank Sta=607,625.84
XS Rating Curve= 0 ,0
Exp/Cntr(USF)=0,0
Exp/Cntr=0.3,0.1
LCMann Table=0

Chan Stop Cuts=-1
Use User Specified Reach Order=0
Composite Channel Slope=5